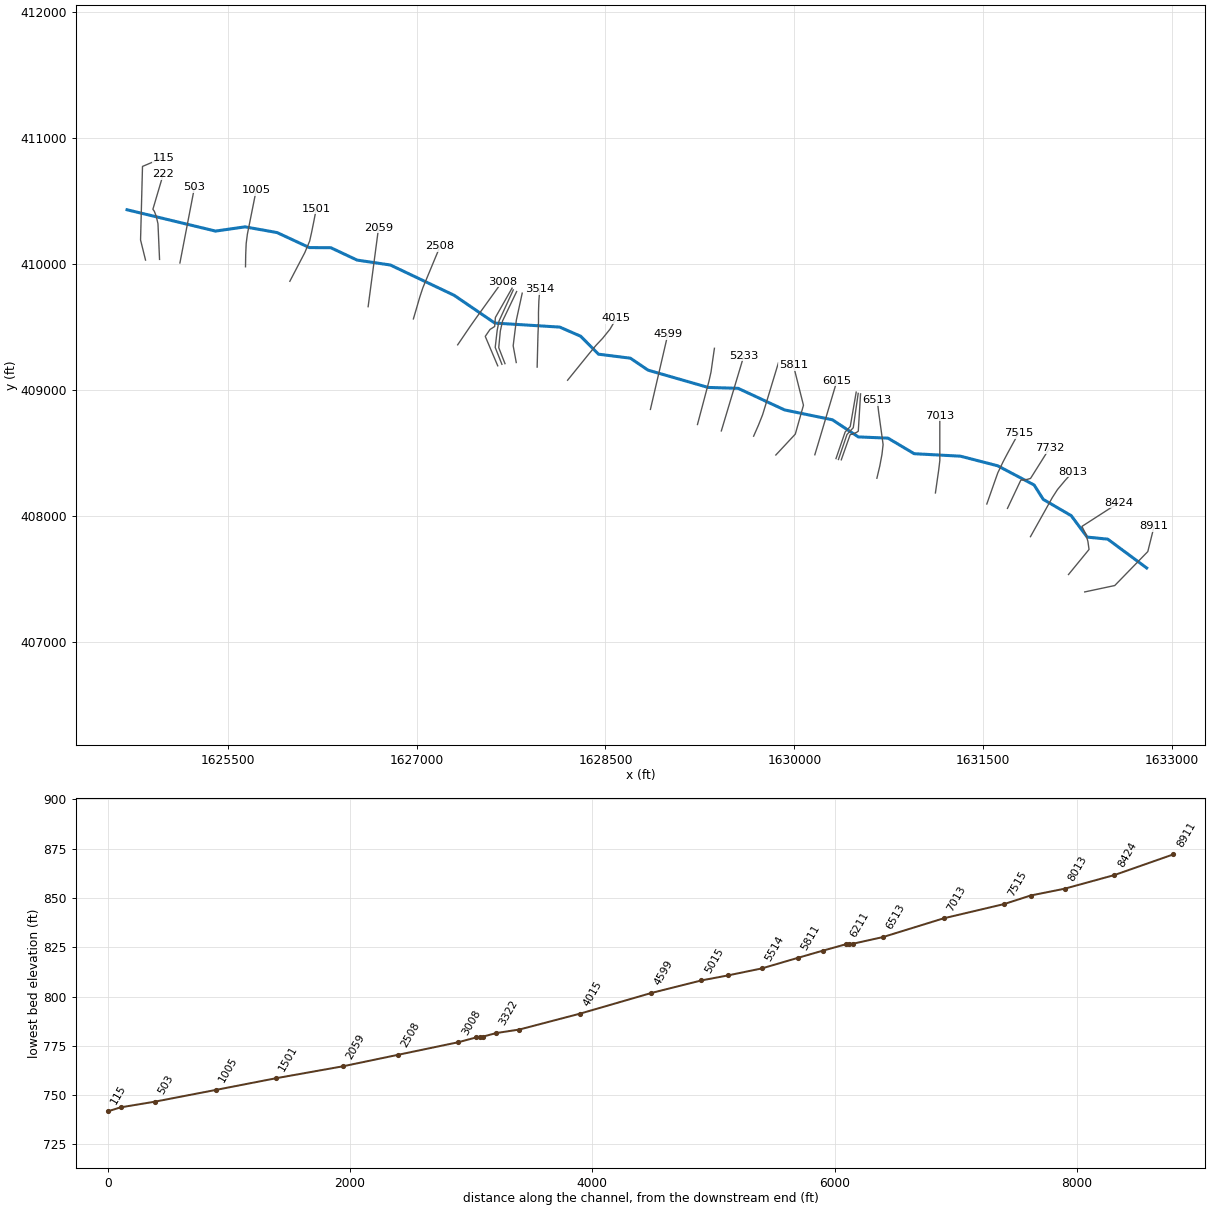
--- HOGRN.prj (project) ---

Proj Title=HOGRN
Current Plan=p01
Default Exp/Contr=0,0
English Units
Geom File=g01
Flow File=f01
Plan File=p01
BEGIN DESCRIPTION:
---------- MODELED AS PART OF WVEMD CTP PROGRAM, 2023----------
Stream Name: Hog Run
Flood Zone:  AFH
Wetzel County, WV
HEC-RAS Version: RAS 6.3
Vertical Datum: NAVD88
Projection: NAD 1983 StatePlane West Virginia S FIPS 4702 (US Feet)
Terrain: 1-meter West Virginia FEMA R3 South Central (collected 2018-2020)
Land Use: 2019 NLCD
Hydrologic Method:
WV SIR2010-5033 regression equations
Additional Model Notes:
None
END DESCRIPTION:
DSS Export Rating Curves= 0
DSS Export Rating Curve Sorted= 0
DSS Export Volume Flow Curves= 0
DXF OffsetX= 0
DXF OffsetY= 0
DXF ScaleX= 0
DXF ScaleY= 0

--- HOGRN.p01 (plan) ---

Plan Title=Floodplain
Program Version=6.30
Short Identifier=Floodplain
Geom File=g01
Flow File=f01
Subcritical Flow
K Sum by GR= 0
Std Step Tol= 0.01
Critical Tol= 0.01
Num of Std Step Trials= 20
Max Error Tol= 0.3
Flow Tol Ratio= 0.001
Split Flow NTrial= 30
Split Flow Tol= 0.02
Split Flow Ratio= 0.02
Log Output Level= 0
Friction Slope Method= 1
Unsteady Friction Slope Method= 2
Unsteady Bridges Friction Slope Method= 1
Parabolic Critical Depth
Global Vel Dist= 0 , 0 , 0
Global Log Level= 0
CheckData=True
Encroach Param=-1 ,0,0, 0
Mapping Interval=1HOUR
Computation Time Step Use Courant=        0
Computation Time Step Use Time Series=    0
Computation Time Step Count To Double=0
Computation Time Step Max Doubling=0
Computation Time Step Max Halving=0
Computation Time Step Residence Courant=0
Run HTab= 0
Run UNet= 0
Run Sediment= 0
Run PostProcess= 0
Run WQNet= 0
Run RASMapper= 0
UNET Theta= 0
UNET Theta Warmup= 0
UNET ZTol= 0
UNET ZSATol= 0
UNET MxIter= 0
UNET Max Iter WO Improvement= 0
UNET MaxInSteps= 0
UNET DtIC= 0
UNET DtMin= 0
UNET MaxCRTS= 0
UNET WFStab= 0
UNET SFStab= 0
UNET WFX= 1
UNET SFX= 1
UNET Gravity=32.17405
UNET 1D Methodology=Finite Difference
UNET DSS MLevel= 1
UNET Pardiso=0
UNET DZMax Abort= 0
UNET Use Existing IB Tables= 0
UNET Froude Reduction=False
UNET Froude Limit= 0
UNET Froude Power= 0
UNET D1 Cores= 0
UNET WindReference=Eulerian
UNET WindDragFormulation=Hsu (1988)
UNET D2 Coriolis=0
UNET D2 Cores= 0
UNET D2 Theta= 1
UNET D2 Theta Warmup= 1
UNET D2 Z Tol= 0.01
UNET D2 Volume Tol= 0.01
UNET D2 Max Iterations= 20
UNET D2 Equation= 0
UNET D2 RampUpFraction=0.1
UNET D2 TimeSlices= 1
UNET D2 Turbulence Formulation=Non-Conservative (original)
UNET D2 Eddy Viscosity=0.3
UNET D2 Transverse Eddy Viscosity=0.1
UNET D2 Smagorinsky Mixing=0
UNET D2 BCVolumeCheck=0
UNET D2 Cores=0
UNET D2 SolverType=PARDISO (Direct)
UNET D2 Minimum Iterations= 3
UNET D2 Maximum Iterations= 30
UNET D2 Restart Number= 10
UNET D2 Relaxation Coeff=1.3
UNET D2 SOR Precondition Iterations= 10
UNET D2 ILUT Maximum Fill= 8
UNET D2 ILUT Tolerance=1E-08
UNET D2 Convergence Tolerance=0.00001
UNET D1D2 MaxIter= 0
UNET D1D2 ZTol=0.01
UNET D1D2 QTol=0.1
UNET D1D2 MinQTol=1
Write IC File= 0
Write IC File at Fixed DateTime=0
Write IC File at Sim End=0
Echo Input=False
Echo Parameters=False
Echo Output=False
Write Detailed= 0
HDF Write Warmup=0
HDF Write Time Slices=0
HDF Flush=0
HDF Compression= 1
HDF Chunk Size= 1
HDF Spatial Parts= 1
HDF Use Max Rows=0
HDF Fixed Rows= 1
Calibration Method= 0
Calibration Iterations= 20
Calibration Max Change=0.05
Calibration Tolerance=0.2
Calibration Maximum=1.5
Calibration Minimum=0.5
Calibration Optimization Method= 1
WQ AD Non Conservative
WQ ULTIMATE=-1
WQ Max Comp Step=1HOUR
WQ Output Interval=15MIN
WQ Output Selected Increments= 0
WQ Output face flow=0
WQ Output face velocity=0
WQ Output face area=0
WQ Output face dispersion=0
WQ Output cell volume=0
WQ Output cell surface area=0
WQ Output cell continuity=0
WQ Output cumulative cell continuity=0
WQ Output face conc=0
WQ Output face dconc_dx=0
WQ Output face courant=0
WQ Output face peclet=0
WQ Output face adv mass=0
WQ Output face disp mass=0
WQ Output cell mass=0
WQ Output cell source sink temp=0
WQ Output nsm pathways=0
WQ Output nsm derived pathways=0
WQ Create Restart=0
WQ Fixed Restart=0
WQ System Summary=0
WQ Write To DSS=0
Sorting and Armoring Iterations= 10
XS Update Threshold= 0.02
Bed Roughness Predictor= 0
Hydraulics Update Threshold= 0.02
Energy Slope Method= 1
Volume Change Method= 1
Sediment Retention Method= 0
Sediment TS Multiplier= 1
Warm Up Method= 0
XS Weighting Method= 0
Number of US Weighted Cross Sections= 1
Number of DS Weighted Cross Sections= 1
Upstream XS Weight=0
Main XS Weight=1
Downstream XS Weight=0
Number of DS XS's Weighted with US Boundary= 1
Upstream Boundary Weight= 1
Weight of XSs Associated with US Boundary= 0
Number of US XS's Weighted with DS Boundary= 1
Downstream Boundary Weight= 0.5
Weight of XSs Associated with DS Boundary= 0.5
Percentile Method= 0
Sediment Output Level= 3
Mass or Volume Output= 0
Output Increment Type= 1
Profile and TS Output Increment= 1
Transport Output Increment 1
XS Output Flag= 0
XS Output Increment= 10
Read HDF5 Sediment Hotstart= 0
Sediment Hotstart Type= 0
Write Gradation File= 0
Read Gradation Hotstart= 0
Write HDF5 File= 1
Write Binary Output= 1
Write DSS Sediment File= 0
DSS Sediment Output Type= 1
SV Curve= 0
Specific Gage Flag= 0
Subcell Erosion Methods= 0
Subcell Deposition Methods= 0
Advection Scheme= 1
Matrix Solver= 0
Implicit Weighting Factor= 1
Maximum Outer Loop Convergence Iterations= 5
Convergence Maximum Absolute= 0.001
Convergence RMSE= 0.0001
Grain Fractions Max Abs Error= 0.001
Max Subgrid Regions= 1
Max Subgrid Length Scale= 3.402823E+38
Initial Layer Thickness= 3.402823E+38
Min Layer Thickness= 3.402823E+38
Max Layer Thickness= 3.402823E+38
Number of Layers= 5

--- HOGRN.f01 (steady flow) ---

Flow Title=Flow
Program Version=4.00
Number of Profiles=1
Profile Names=F01pct
River Rch & RM=HOGRN,Main,8911
     653
River Rch & RM=HOGRN,Main,7732
     733
River Rch & RM=HOGRN,Main,5811
     836
River Rch & RM=HOGRN,Main,3211
     942
Boundary for River Rch & Prof#=HOGRN,Main      ,1
Up Type=0
Dn Type=3
Dn Slope=0.011696

--- HOGRN.g01 (geometry) ---

Geom Title=Geometry
Program Version=6.31

River Reach=HOGRN           ,Main
Reach XY= 30
     1632798.417      407584.079     1632489.348      407812.735
     1632325.766      407829.212     1632199.032      407999.358
     1631977.071      408128.543     1631904.251      408243.025
     1631615.072      408395.316     1631319.592      408471.637
     1630951.991      408491.242     1630744.035      408614.826
1630508.29804628408624.625034713     1630302.914      408760.466
      1629922.71      408838.887     1629553.359      409010.434
     1629315.644      409017.436     1628838.464      409154.674
     1628698.426       409249.55     1628444.957      409281.408
     1628302.818      409424.2471628137.11820276409496.567475734
     1627621.182      409528.576     1627298.743      409748.786
1626791.71764156409989.5880666151626527.67968043410028.486516247
1626319.04979565410126.7405889571626148.62154292 410127.88632511
     1625892.409      410246.9721625637.82643404410292.452378649
     1625403.676      410258.875       1624700.4      410428.316

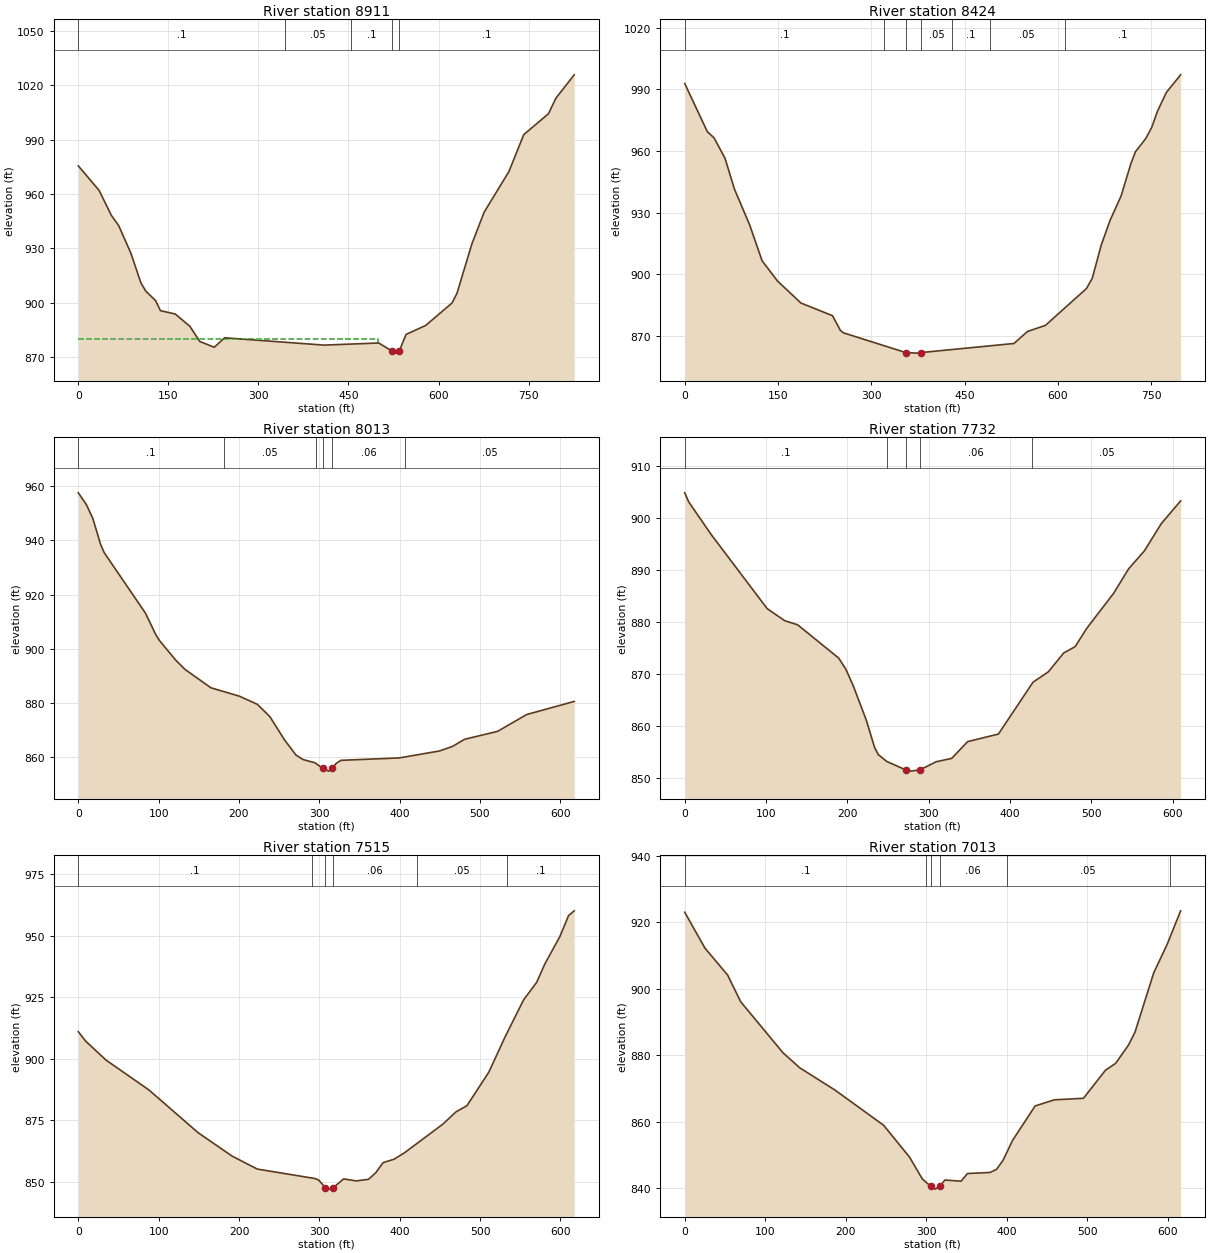
Type RM Length L Ch R = 1 ,8911    ,478.9,486.5,499.1
XS GIS Cut Line= 4
1632306.28034589407393.8316477091632544.61235541407444.540585904
1632807.28465526407714.3121371021632856.97941469407914.105353591
#Sta/Elev= 30
       0  975.56    34.6  962.02      55  948.25    67.3  942.54    87.8  927.14
   104.1  911.03   112.3  906.42   128.7  901.15   136.8   895.6   161.4  893.77
   185.9  886.94   202.3  878.58   226.4   875.4   243.7  880.61   409.2  876.58
   500.5  877.74   522.8  873.25   528.4  872.15   534.5  873.26     546  882.49
   578.6  887.42   622.5  899.82   630.7  905.12   655.7  932.58   676.1  950.03
   717.3  972.43     742  992.81   783.2 1004.37   795.6 1012.97826.0758 1025.85
#Mann= 5 ,-1,0
       0      .1       0  343.67     .05       0  453.67      .1       0
   522.8    .045       0   534.5      .1       0
#XS Ineff= 2 , 0
             500  879.77
Permanent Ineff=
       F       F
Bank Sta=522.8,534.5
XS Rating Curve= 0 ,0
Exp/Cntr(USF)=0,0
Exp/Cntr=0.3,0.1

Type RM Length L Ch R = 1 ,8424    ,416,411.1,397.4
BEGIN DESCRIPTION:
Low water crossing
END DESCRIPTION:
XS GIS Cut Line= 6
 1632177.4922187407532.0347006271632340.51587701407730.990104039
1632331.86564208407793.5379566161632315.89597759407850.762587698
1632283.95664861407913.9758429631632575.40302552408101.619400695
#Sta/Elev= 30
       0  992.81    36.3   969.4    47.2  966.35    64.8  956.42    79.9  941.47
   104.1  924.27   124.4  906.58   149.3   896.7   186.8  886.05   237.6  879.87
   250.3  872.72   255.2  871.53   355.4  861.94   373.5  861.66   379.9  861.93
   529.4  866.35   551.2  872.19   580.1  875.17   646.1  893.11   655.4  898.08
   669.8  914.25   684.1  926.31   701.7  938.09   717.4  953.76   724.8  959.62
   741.2  965.96   750.9  971.43   760.2  979.31   774.5  988.48797.4485  997.04
#Mann= 7 ,-1,0
       0      .1       0  320.52     .05       0   355.4    .045       0
   379.9     .05       0  429.27      .1       0  490.82     .05       0
  610.82      .1       0
Bank Sta=355.4,379.9
XS Rating Curve= 0 ,0
Exp/Cntr(USF)=0,0
Exp/Cntr=0.3,0.1

Type RM Length L Ch R = 1 ,8013    ,286.1,280.8,272.5
XS GIS Cut Line= 6
1631875.29976568407832.4785963451631963.77695093407990.666272089
1632049.20296118408143.3995624181632089.86856225408206.588740513
1632147.30184634408275.2178683431632211.56943434408347.282356754
#Sta/Elev= 30
       0  957.59     9.9   953.3    18.1  948.08    27.6  938.63    32.1  935.52
    83.6  913.11    96.3  905.24   100.9  903.04   121.1   895.8   132.8  892.32
   165.1  885.52   200.5  882.43   222.9  879.41   238.4   874.9   256.7  866.27
     271  860.65   279.9  858.99   294.6  857.81  304.29855.7333   311.7  854.72
   316.3  855.72   320.9  857.56   326.9  858.71   399.7   859.6   449.6  862.17
   466.1  863.88   480.9  866.49   522.1  869.43   558.2  875.64   617.4  880.48
#Mann= 6 ,-1,0
       0      .1       0  181.25     .05       0  296.25     .06       0
  304.29    .045       0   316.3     .06       0  406.25     .05       0
Bank Sta=304.29,316.3
XS Rating Curve= 0 ,0
Exp/Cntr(USF)=0,0
Exp/Cntr=0.3,0.1

Type RM Length L Ch R = 1 ,7732    ,211.4,217.7,224.8
XS GIS Cut Line= 6
1631692.77963135408057.2969277151631798.95793812408282.049993301
1631822.67288988408282.0499933011631853.93350812408288.517707419
1631876.03153135408294.9854215361632026.40588459408534.290843887
#Sta/Elev= 30
       0  904.81     4.9  903.07      32   896.9   101.4  882.53     123  880.21
   138.9  879.42   189.4  873.01   198.2  870.86   207.1  867.75   223.2  861.13
   233.6  855.79   238.1  854.44   248.6  853.12   272.2  851.49   277.8  851.27
   289.1   851.5   309.2  853.07   328.4  853.73     348  856.95   385.8   858.4
   428.3  868.37   447.2  870.37   466.1     874   480.2  875.22   494.4  878.73
   527.5  885.48     546   890.2   565.3  893.63   586.1  898.88   609.9  903.26
#Mann= 5 ,-1,0
       0      .1       0  248.57     .06       0   272.2    .045       0
   289.1     .06       0  427.23     .05       0
Bank Sta=272.2,289.1
XS Rating Curve= 0 ,0
Exp/Cntr(USF)=0,0
Exp/Cntr=0.3,0.1

Type RM Length L Ch R = 1 ,7515    ,499.2,501.4,503.5
XS GIS Cut Line= 6
1631528.77519625408091.9482217581631615.36754276408338.050091758
1631658.61187884408428.2644782511631693.54816067408494.633111924
1631735.42110842408571.4886012521631780.76255317408653.587190345
#Sta/Elev= 30
       0  910.98     9.1  907.16    34.5  899.43    87.8  887.31     149  869.93
   191.4  860.38   222.7  855.11   294.7  851.25   299.3  850.59  307.42847.5898
   312.4  846.95   317.3  847.53   330.2  851.11   345.9  850.29   361.2  850.95
   370.3  853.66   379.3  857.73   392.9   859.1   406.4  861.84     454  873.46
     470  878.37   483.7   880.9     511  894.57   530.6  908.49   554.2  923.93
   570.4  931.03   580.7  938.58   599.4   949.7   610.1  958.19   617.2  960.15
#Mann= 6 ,-1,0
       0      .1       0  290.89     .06       0  307.42    .045       0
   317.3     .06       0  420.94     .05       0  533.46      .1       0
Bank Sta=307.42,317.3
XS Rating Curve= 0 ,0
Exp/Cntr(USF)=0,0
Exp/Cntr=0.3,0.1

Type RM Length L Ch R = 1 ,7013    ,498.6,500.4,499.3
XS GIS Cut Line= 6
1631120.59687875408179.7469306741631133.89442433408273.713278174
  1631146.589937408361.4870527541631155.57089017408436.982964754
1631155.46754393408537.0414916721631155.46754393408793.291307256
#Sta/Elev= 30
       0  922.97      25  912.22    53.3  904.06    69.5  896.05     122   880.7
   142.9  876.16   186.7  869.46   247.1  858.87   279.2   849.3   295.2   842.7
  305.41840.5543   311.2  839.67  316.78840.5585   323.2  842.41   343.2  842.05
   351.2  844.37   379.2  844.68   387.2  845.59   395.2  848.29   407.2  854.34
   435.2   864.7   459.2  866.54   495.2     867   522.5  875.43   535.2  877.52
   551.2  883.03   559.2  886.87   582.5  904.74   599.2  913.33   615.9   923.4
#Mann= 6 ,-1,0
       0      .1       0  299.62     .06       0  305.41    .045       0
  316.78     .06       0  399.68     .05       0  602.18      .1       0
Bank Sta=305.41,316.78
XS Rating Curve= 0 ,0
Exp/Cntr(USF)=0,0
Exp/Cntr=0.3,0.1

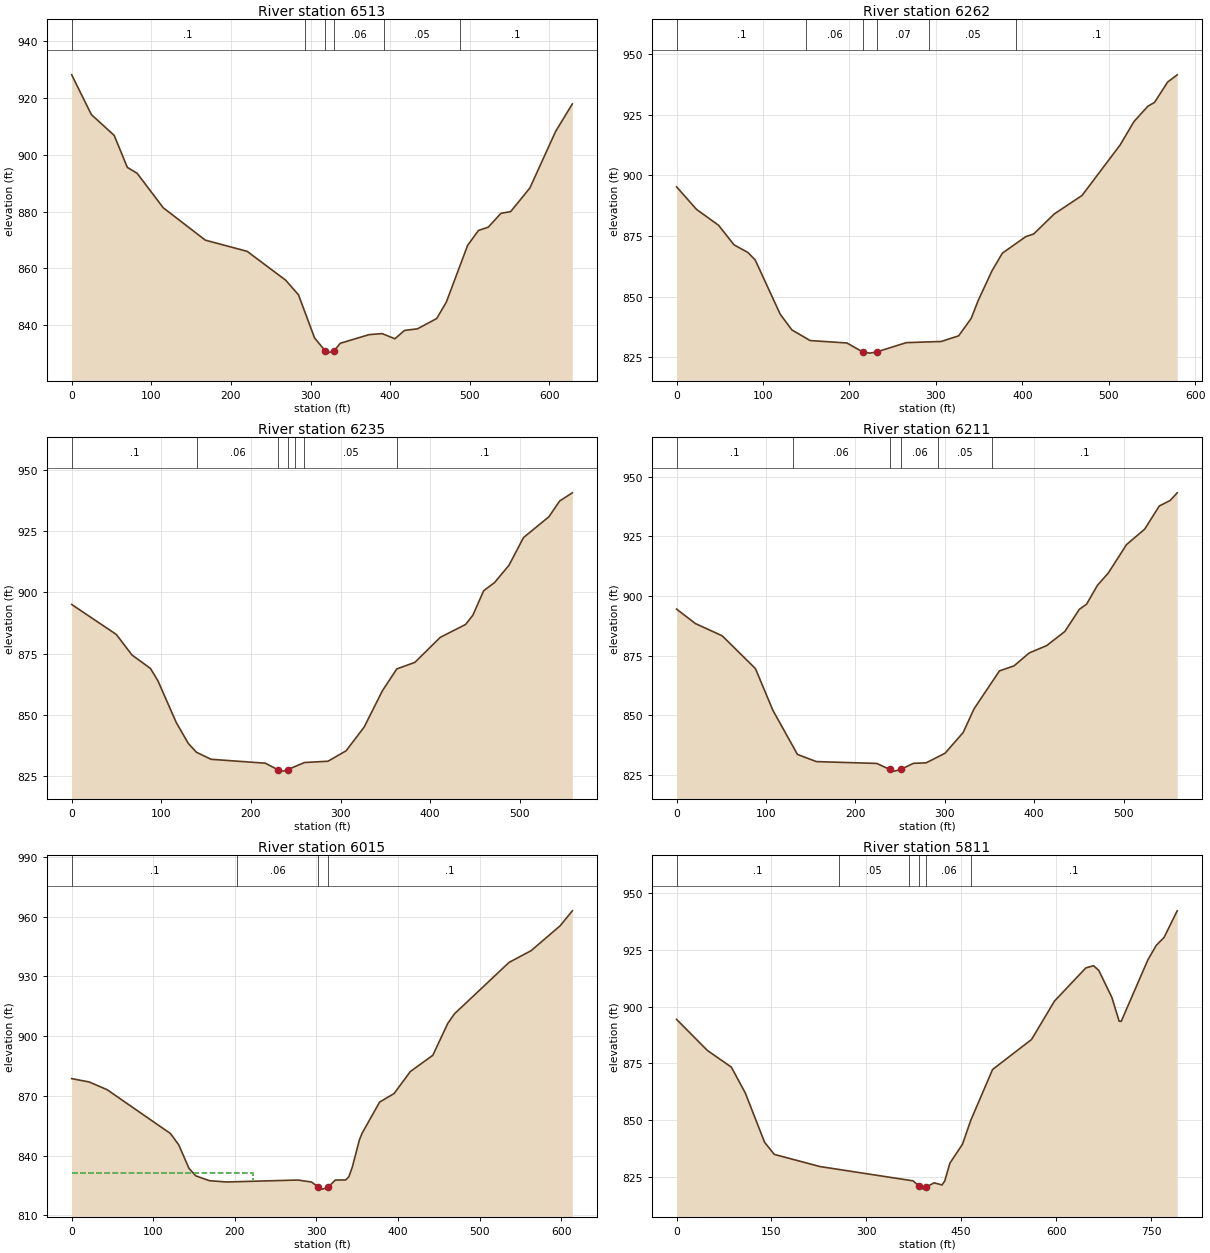
Type RM Length L Ch R = 1 ,6513    ,261.9,250.8,243.3
XS GIS Cut Line= 6
1630655.67917342408296.5459096731630678.70438984408393.319338173
 1630696.0045521 408485.365085841630705.10525568408564.279954255
1630669.30906743 408824.338161171630658.48330167408917.491190091
#Sta/Elev= 30
       0  928.11    24.7  914.13    53.4  906.79    69.9  895.54    82.2  893.46
     115  881.33   167.9  869.93   220.5  865.98   268.8  855.84   284.9   850.7
   305.1  835.51   318.2  831.06   321.2  830.17  329.84  831.06   337.4  833.64
   373.5  836.67   389.9  837.05     406  835.23   418.1  838.16   434.3  838.72
   458.5  842.34   470.6  848.11   497.4  868.11     511  873.35   523.2  874.48
   539.3  879.38   551.4  879.97   575.6   888.3   607.8  908.13   628.9  917.87
#Mann= 6 ,-1,0
       0      .1       0  292.57     .06       0   318.2    .045       0
  329.84     .06       0  392.57     .05       0  487.58      .1       0
Bank Sta=318.2,329.84
XS Rating Curve= 0 ,0
Exp/Cntr(USF)=0,0
Exp/Cntr=0.3,0.1

Type RM Length L Ch R = 1 ,6262    ,21.4,26.7,29.4
BEGIN DESCRIPTION:
Structure XS 4. Low water crossing
END DESCRIPTION:
XS GIS Cut Line= 6
 1630372.9304017408442.7437521681630443.46308652408642.364558267
1630471.40999937408651.0147931981630494.03369073408660.330430816
1630508.00714716408670.3114711211630525.97301971408966.415666834
#Sta/Elev= 30
       0  895.28    23.1  885.98    48.6  879.44    66.6  871.34    82.5  868.24
      91  865.14   119.9  842.81   133.4  836.33   154.6  831.93   197.1  830.93
   215.5  827.23   223.6  826.75  231.35827.2209   265.8  831.07   306.2  831.55
   326.4  833.88   340.9  841.04     349  848.42     365  860.68     377  867.95
   404.3   874.8   413.1  875.81   437.1  884.12   469.2  891.72   513.3  912.56
   529.3  922.18   545.3  928.47   553.1  930.08   568.2  938.44   579.3  941.43
#Mann= 6 ,-1,0
       0      .1       0     150     .06       0   215.5    .045       0
  231.35     .07       0  292.61     .05       0  392.61      .1       0
Bank Sta=215.5,231.35
XS Rating Curve= 0 ,0
Exp/Cntr(USF)=0,0
Exp/Cntr=0.3,0.1

Type RM Length L Ch R = 1 ,6235    ,24.2,24.2,24.1
BEGIN DESCRIPTION:
Structure XS 3
END DESCRIPTION:
XS GIS Cut Line= 4
1630350.30671034408445.4053629161630418.17778441408643.695363641
1630468.08298594408697.5929812871630507.34174447408970.408082956
#Sta/Elev= 30
       0   895.1    49.8  882.83    67.3  874.42    87.9  868.92    96.3  863.81
   116.7  846.79   130.1  838.24   139.3   834.6   155.5  831.74   216.2  830.13
   230.1  827.46     236  826.89   241.1 827.504   259.7  830.41     286  830.94
   306.2   835.2   326.4  844.93   346.6  859.69   362.8  868.71     383  871.41
   411.3  881.64   439.6  886.92   447.7  890.71   459.8  900.74   471.9  904.06
   488.1  911.19   504.2  922.48   532.5  930.97   544.6  937.46   558.7  940.79
#Mann= 7 ,-1,0
       0      .1       0     140     .06       0   230.1    .045       0
   241.1     .06       0  249.58     .07       0  259.58     .05       0
  363.04      .1       0
Bank Sta=230.1,241.1
XS Rating Curve= 0 ,0
Exp/Cntr(USF)=0,0
Exp/Cntr=0.3,0.1

Type RM Length L Ch R = 1 ,6211    ,193.8,196.7,199.5
BEGIN DESCRIPTION:
Structure XS 2
END DESCRIPTION:
XS GIS Cut Line= 4
1630331.01003242408452.724792473 1630403.5389253408663.657444251
1630444.12848921408706.9086189051630491.37207998 408980.38912326
#Sta/Elev= 30
       0  894.54      21   888.5    51.1  883.32    88.2  869.59   107.7  852.12
   135.2   833.6   156.3  830.59   223.9  829.82   238.2  827.35   243.9  826.59
  250.98827.3649   264.8  829.86   279.1  830.06   300.3   834.1   320.6  842.83
   332.7  852.73   361.1  868.62   377.4  870.74   394.5  876.17   413.9  879.23
   434.2  885.14   450.4  894.42   458.6  896.63   470.7  904.53   482.9   909.7
   503.2  921.59   523.5  928.05   539.9  937.79   551.9  940.06   559.9   943.3
#Mann= 6 ,-1,0
       0      .1       0     130     .06       0   238.2    .045       0
  250.98     .06       0  292.37     .05       0  352.37      .1       0
Bank Sta=238.2,250.98
XS Rating Curve= 0 ,0
Exp/Cntr(USF)=0,0
Exp/Cntr=0.3,0.1

Type RM Length L Ch R = 1 ,6015    ,203.5,203.8,203.8
BEGIN DESCRIPTION:
Structure XS 1
END DESCRIPTION:
XS GIS Cut Line= 6
1630162.78613034408482.8903532621630190.30772884 408573.80552575
 1630215.3165371408657.655423671 1630236.7515336408729.526999086
1630286.76718159408897.2274510861630338.56891526409070.917392418
#Sta/Elev= 30
       0  878.69    21.6  876.99    43.5  873.12   121.1  851.12   131.2  845.48
   143.8  833.65   152.1   829.9   168.8  827.48   189.7  826.82   277.3  827.79
     294   826.8   302.4  824.22   307.6  823.23   314.1  824.16   323.2  827.79
   335.8  827.84   339.8  829.47   344.1  834.44   352.6  847.81   355.9  851.22
   377.5  866.93   395.2   871.2   415.1  882.24   442.7  890.41     461   906.4
   469.3  911.25   536.1     937   563.2  942.92   598.7  955.37   613.7   962.9
#Mann= 4 ,-1,0
       0      .1       0  202.49     .06       0   302.4    .045       0
   314.1      .1       0
#XS Ineff= 2 , 0
          222.24  831.27
Permanent Ineff=
       F       F
Bank Sta=302.4,314.1
XS Rating Curve= 0 ,0
Exp/Cntr(USF)=0,0
Exp/Cntr=0.3,0.1

Type RM Length L Ch R = 1 ,5811    ,296.2,296.3,295.8
XS GIS Cut Line= 4
1629853.20120247408481.0383339351630007.74587314408646.799956508
1630072.55492858408876.1243065331629992.78993727409192.691615808
#Sta/Elev= 30
       0  894.39    48.5  880.75    86.6  873.35   108.7  861.94   139.2  840.23
   154.5  834.93   226.6  829.58   373.9  823.27   383.9  820.79   390.4  819.63
   394.7  820.58   407.2  822.41   419.6  821.47   423.8  823.15   432.1  831.07
     452  839.44   464.9   849.8   499.5   872.3   561.2  885.54   597.4  902.43
   646.9  917.03   659.2  918.02   667.5  915.92   688.1  904.07   699.6  893.58
   702.9  893.51     745  920.57   758.2  926.94   770.6  930.47   791.4  942.18
#Mann= 6 ,-1,0
       0      .1       0  256.63     .05       0  366.63     .06       0
   383.9    .045       0   394.7     .06       0  464.94      .1       0
Bank Sta=383.9,394.7
XS Rating Curve= 0 ,0
Exp/Cntr(USF)=0,0
Exp/Cntr=0.3,0.1

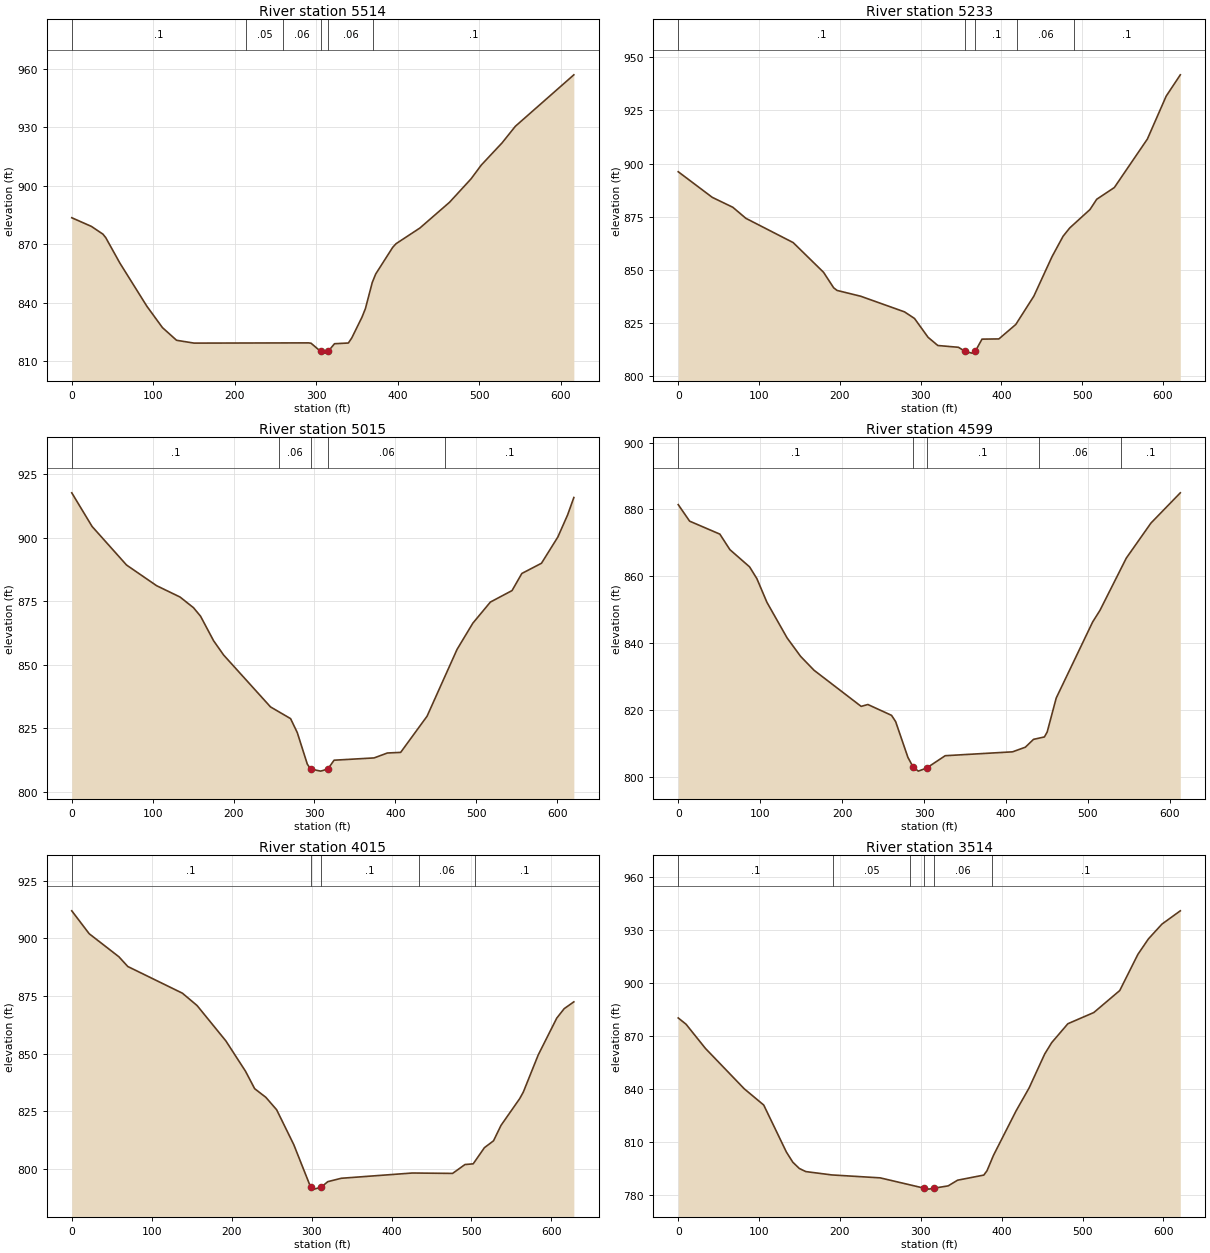
Type RM Length L Ch R = 1 ,5514    ,280.6,281.2,281.3
XS GIS Cut Line= 6
1629676.75888717408630.461908504  1629715.002249408717.514227837
1629747.83748518408800.0980521741629770.08219133408872.348563835
1629799.30030876408968.0412858431629873.64956951 409213.14315784
#Sta/Elev= 30
       0  883.64    24.1   879.2    38.2  875.24    41.6   873.5    59.1  860.34
    92.1  838.31   111.2  827.35   128.5  820.86     150  819.41   290.2  819.53
   293.4  819.36  305.15815.1835   309.9  814.28  314.59815.2656   322.2   819.1
   339.2  819.46   343.4  822.08   355.9  832.71   360.1  837.09   368.5  850.49
   372.7   854.8   393.6  868.49   397.7  870.35     427   878.4   463.3  891.58
   489.7  903.59   502.2  910.63   527.8  922.05     544  930.51   615.7  956.86
#Mann= 6 ,-1,0
       0      .1       0  213.95     .05       0  259.55     .06       0
  305.15    .045       0  314.59     .06       0  369.61      .1       0
Bank Sta=305.15,314.59
XS Rating Curve= 0 ,0
Exp/Cntr(USF)=0,0
Exp/Cntr=0.3,0.1

Type RM Length L Ch R = 1 ,5233    ,218.9,218.7,218.2
XS GIS Cut Line= 2
1629420.29456077408672.2342795481629598.78103824409267.702096643
#Sta/Elev= 30
       0  896.13    42.1  884.08    67.6  879.39    83.8  874.18   142.3  862.77
   179.9  848.78   192.4  841.49   196.6  840.24   225.8  837.51   280.1  830.15
   292.5  827.04   309.3  818.17   321.4   814.3   346.9  813.46   355.3  811.52
   363.6  810.71   367.9811.6739   376.1   817.3     397   817.4   417.9   824.2
   440.3  837.56   462.7  856.08   476.4  865.71   484.7  869.66   509.8  878.35
   518.1  883.17   539.9  888.68   580.8  911.51   604.1  931.73   621.6  941.77
#Mann= 5 ,-1,0
       0      .1       0   355.3    .045       0   367.9      .1       0
     420     .06       0     490      .1       0
Bank Sta=355.3,367.9
XS Rating Curve= 0 ,0
Exp/Cntr(USF)=0,0
Exp/Cntr=0.3,0.1

Type RM Length L Ch R = 1 ,5015    ,414.1,415.6,414.4
XS GIS Cut Line= 6
1629230.81784992408723.096565753 1629254.8578281408813.711870089
1629322.17101367409067.434459761 1629338.6214401409141.273879007
1629351.35468234409231.1142505111629365.42059909 409328.20362325
#Sta/Elev= 30
       0  917.73    25.1   904.5    67.7  889.31   104.9  881.17   133.9   876.7
   150.5   872.5   159.2  869.16   175.3  859.52   187.7  853.89   245.7  833.45
   270.5  828.84   278.8  823.34   291.2  810.92   295.3     809   307.7  808.17
  316.54808.9816   324.3  812.47   373.8  813.37   390.2  815.31   406.6  815.55
   439.2  829.77   476.3  856.08   495.8   866.4   517.5  874.72   544.3  879.25
   556.4  885.98   580.7  890.01   600.9  900.32     613  909.04   620.7  915.88
#Mann= 5 ,-1,0
       0      .1       0  256.25     .06       0   295.3    .045       0
  316.54     .06       0   461.9      .1       0
Bank Sta=295.3,316.54
XS Rating Curve= 0 ,0
Exp/Cntr(USF)=0,0
Exp/Cntr=0.3,0.1

Type RM Length L Ch R = 1 ,4599    ,585.7,583.9,579.3
XS GIS Cut Line= 2
 1628857.1389508408843.027374374 1628995.6198385409440.033867999
#Sta/Elev= 30
       0  881.45    13.9  876.51    50.8  872.63    63.1  867.98    87.1  862.84
      96  859.32   108.3  852.23   132.9  841.59   149.4  836.07   165.8  831.92
   223.3  821.12   231.5  821.68   260.4  818.44   265.4  816.57   280.4  805.86
   286.8802.9687   293.1  801.76   303.2802.6856   325.9  806.37   408.1  807.53
   423.7  808.91   433.7  811.26     447  811.98   450.4  813.47   461.4  823.61
   505.9  846.37   514.8  849.83     547  865.47     577  875.92   612.9  884.98
#Mann= 5 ,-1,0
       0      .1       0   286.8    .045       0   303.2      .1       0
     440     .06       0     540      .1       0
Bank Sta=286.8,303.2
XS Rating Curve= 0 ,0
Exp/Cntr(USF)=0,0
Exp/Cntr=0.3,0.1

Type RM Length L Ch R = 1 ,4015    ,496.2,501.6,504.6
XS GIS Cut Line= 6
1628199.32942735409074.6762431711628360.55810751 409273.84808892
1628424.53009242409351.1005590861628477.71961859409407.735616416
1628535.85598525409479.6265487521628587.38147275409566.964628667
#Sta/Elev= 30
       0  911.91    21.8  901.99      59     892    70.1  887.79   138.4  876.23
   156.8  870.87   192.8  855.55   217.4  842.39   228.8  834.86   242.8  831.12
   256.3  825.73   277.7  810.65  298.84  792.21   303.3  791.35     312  792.21
   320.3  794.58   337.1  796.05   426.1  798.33   476.4  798.16   491.9     802
   502.2  802.31   516.2   809.3   527.6  812.28     537  818.98   560.3  830.52
   564.9   833.4   583.5  849.45   606.7  865.42     616  869.52   628.1  872.48
#Mann= 5 ,-1,0
       0      .1       0  298.84    .045       0     312      .1       0
  434.25     .06       0  504.25      .1       0
Bank Sta=298.84,312
XS Rating Curve= 0 ,0
Exp/Cntr(USF)=0,0
Exp/Cntr=0.3,0.1

Type RM Length L Ch R = 1 ,3514    ,191.5,192,191
XS GIS Cut Line= 6
 1627957.6376535409178.9142236711627964.04118401409435.084315002
1627968.27870834 409536.561146171627968.15764558409613.588223085
1627971.21735075409703.4190801681627978.54640435409799.260752007
#Sta/Elev= 30
       0  880.24     9.6  876.72    33.6     863    81.6  840.12   105.7  830.91
   133.7  804.31   141.7   798.5   149.7  794.98   157.7  793.21   189.7  791.32
   249.7  789.65  303.95783.8162   309.7  783.27   316.2  783.79   333.8  785.12
   345.4  788.33   377.8  791.22   381.8   793.7   389.8  802.42   417.7  827.56
   433.8  840.56   453.1   859.8   461.8  866.28   481.8  876.98   513.8   883.3
   545.9  895.76   568.4  916.31   581.4  925.04   598.1  933.41   620.8  940.93
#Mann= 6 ,-1,0
       0      .1       0  191.25     .05       0  286.25     .06       0
  303.95    .045       0   316.2     .06       0  387.82      .1       0
Bank Sta=303.95,316.2
XS Rating Curve= 0 ,0
Exp/Cntr(USF)=0,0
Exp/Cntr=0.3,0.1

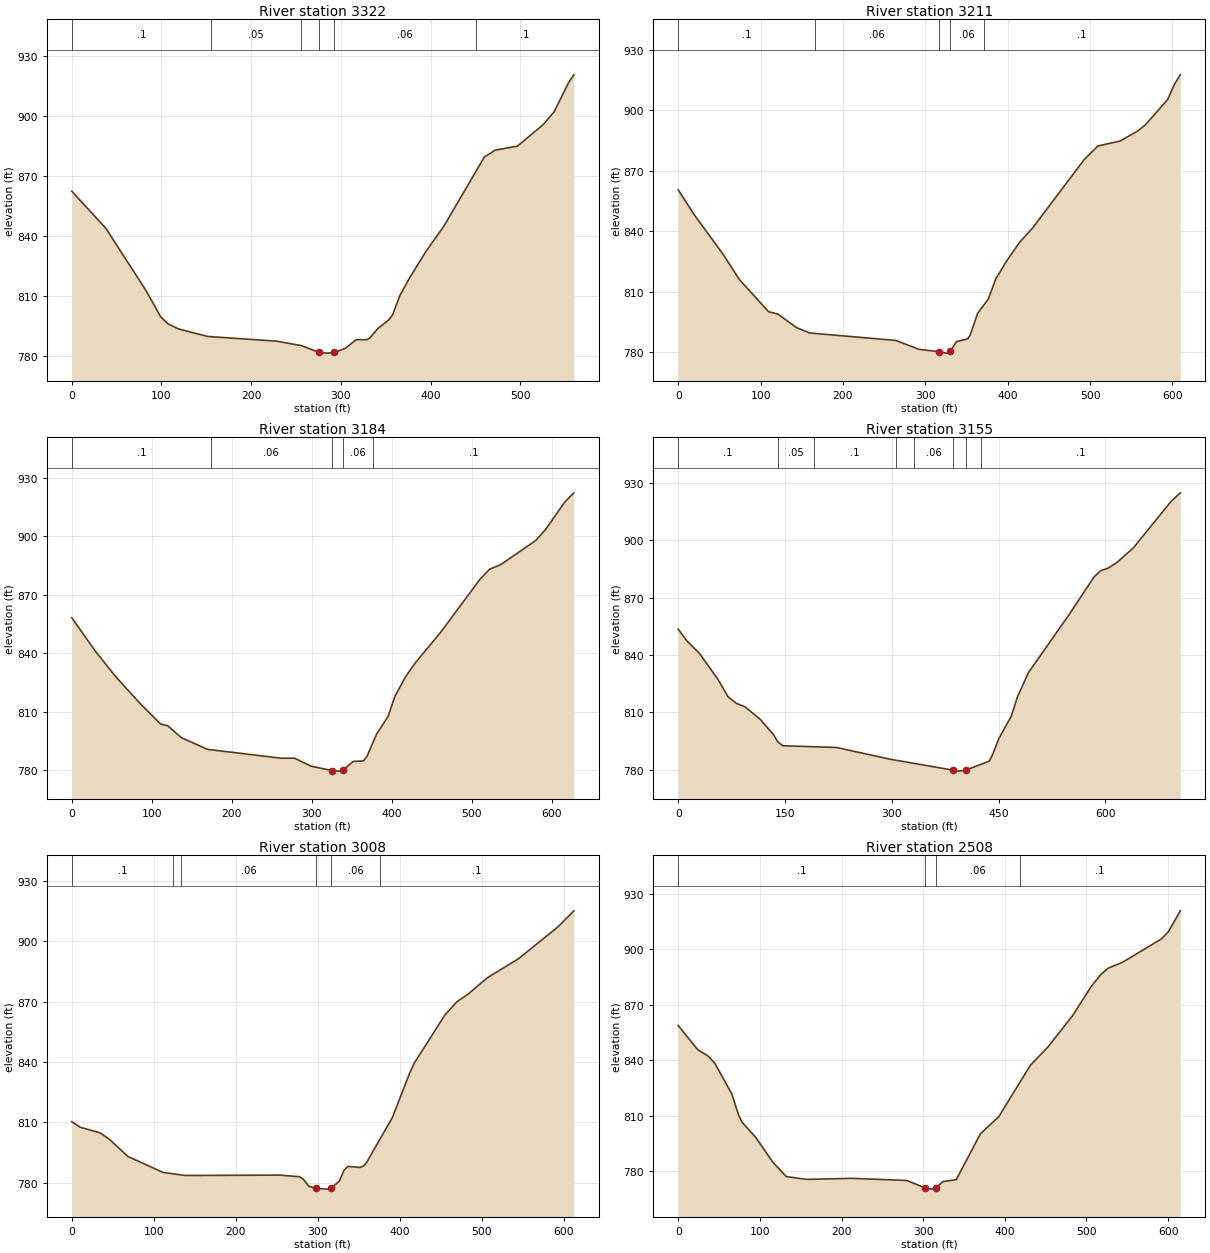
Type RM Length L Ch R = 1 ,3322    ,111.9,110.7,110.3
BEGIN DESCRIPTION:
Structure XS 4
END DESCRIPTION:
XS GIS Cut Line= 4
1627791.58832384409215.1867924941627767.19022532409348.267329893
1627792.32766016409551.5848175871627838.90584825409765.992350063
#Sta/Elev= 30
       0  862.55      38  843.98    82.7  812.85      99  799.74   107.1  796.18
   119.3  793.54   151.7  789.81   228.3  787.47   256.5  785.17   275.5781.8522
   284.7  781.47   292.8  781.84   304.8  783.84   316.9   788.2     329   788.2
   332.3  789.06   341.1  793.75   353.4  798.16   357.5  800.58   365.7  810.31
   376.8  819.35   394.6  832.28   414.8  845.08   459.8  879.63   471.9   883.1
   496.7  885.12   525.3  895.82   537.6  902.31     554  917.16   559.6  920.82
#Mann= 6 ,-1,0
       0      .1       0   155.3     .05       0   255.3     .06       0
   275.5    .045       0   292.8     .06       0  450.16      .1       0
Bank Sta=275.5,292.8
XS Rating Curve= 0 ,0
Exp/Cntr(USF)=0,0
Exp/Cntr=0.3,0.1

Type RM Length L Ch R = 1 ,3211    ,26.8,26.9,27.1
BEGIN DESCRIPTION:
Structure XS 3
END DESCRIPTION:
XS GIS Cut Line= 5
1627702.12862926409206.3147566671627652.59309589409333.480603516
1627665.16181331409465.8218045961627682.90588497409545.670127035
1627794.54566912409778.561067484
#Sta/Elev= 30
       0  860.54    19.6  848.09    53.9  828.98    74.3  816.07   109.7  800.15
   120.7  799.06   143.6   792.3   159.6  789.62   264.1  785.94   292.7  781.48
   316.5  780.37   325.5  779.64   330.1780.4731   337.8  785.33   351.3  786.73
   354.4  788.55   363.3  799.22   376.6  806.58   385.4  816.37   399.2  825.61
   414.2  834.44   429.8  841.44   492.8  875.54   509.6   882.3   536.3  884.71
   557.6  889.63   567.2  892.79   593.9  905.17   602.8  913.11   609.5  917.53
#Mann= 5 ,-1,0
       0      .1       0  166.47     .06       0   316.5    .045       0
   330.1     .06       0  371.21      .1       0
Bank Sta=316.5,330.1
XS Rating Curve= 0 ,0
Exp/Cntr(USF)=0,0
Exp/Cntr=0.3,0.1

Type RM Length L Ch R = 1 ,3184    ,28.1,28.7,30.6
BEGIN DESCRIPTION:
Structure XS 2
END DESCRIPTION:
XS GIS Cut Line= 5
1627677.73053073409201.1394024351627624.49831577409334.959276153
1627640.02437847409470.2578225091627654.81110485409544.930790717
1627767.92956164409791.869121224
#Sta/Elev= 30
       0  858.24    29.5  841.06    55.3  827.84    85.4  814.23   111.3  803.62
   119.9  802.83   137.1  796.67   169.8  790.67   262.4  786.11   278.5  786.16
   299.2  782.06  325.05779.8156   333.3   779.5  338.71779.8318   351.8  784.45
   364.7  784.76   369.1  787.01   381.2  798.47   395.5  807.51   404.3  818.07
   417.5  827.95   429.4  834.94   461.5  850.83   510.9  878.17   522.7  883.16
   536.3  885.42   580.4  897.91   592.4  903.44   616.5  917.58   627.9  922.33
#Mann= 5 ,-1,0
       0      .1       0  174.02     .06       0  325.05    .045       0
  338.71     .06       0  376.33      .1       0
Bank Sta=325.05,338.71
XS Rating Curve= 0 ,0
Exp/Cntr(USF)=0,0
Exp/Cntr=0.3,0.1

Type RM Length L Ch R = 1 ,3155    ,150,146.8,140.6
BEGIN DESCRIPTION:
Low water crossing. Also Structure XS 1
END DESCRIPTION:
XS GIS Cut Line= 6
1627644.46039638409189.3100213331627545.38932965409422.940298101
1627583.09548192409477.6511856981627620.06229786409501.309947903
1627625.97698841409573.0255708341627758.31818949409805.916511283
#Sta/Elev= 30
       0  853.52    12.2  847.45    29.6  840.96    55.6   827.4    69.8  818.25
    81.7  814.71    94.3   812.8   115.6  806.21   133.8  798.36     140  794.53
   146.9  792.53   222.4  791.62   297.6  785.48   386.3  779.73   394.3  779.24
   403.8  779.75   436.8  784.46   441.3  787.71   450.5  796.37   467.8  808.04
   476.6  818.26   491.9  830.82   547.2  860.19     584  880.88   593.2  884.15
   603.5  885.45   616.2  888.46   639.2  896.09   692.6   920.6   705.2  924.92
#Mann= 8 ,-1,0
       0      .1       0     140     .05       0     190      .1       0
  305.53     .05       0  331.09     .06       0   386.3    .045       0
   403.8     .06       0  425.34      .1       0
Bank Sta=386.3,403.8
XS Rating Curve= 0 ,0
Exp/Cntr(USF)=0,0
Exp/Cntr=0.3,0.1

Type RM Length L Ch R = 1 ,3008    ,498.3,500,501.8
XS GIS Cut Line= 6
1627326.46404709409355.8482530121627379.17457159 409433.45669359
1627428.37132359409505.8541865941627471.59138151 409567.15262042
 1627529.9852936409648.3325761711627679.61786833409856.356766418
#Sta/Elev= 30
       0  810.36    10.3  807.58    34.7  804.79    45.7  801.69    68.5  793.06
   111.1  785.18   138.2  783.62   253.2  783.79   277.8     783   282.7  781.69
   289.2  778.26   297.5  777.22   312.3  776.82  316.31777.2308   326.5  780.87
   332.2  786.21   336.9  788.14   351.7  787.59   356.4  788.44     360  790.28
   391.1  812.36   412.5  834.72   418.1  839.62   455.1  863.31   469.9  869.98
   483.3  873.69     507  881.91   544.9  891.33   592.9  907.12   612.6   915.2
#Mann= 6 ,-1,0
       0      .1       0  123.82     .05       0  133.82     .06       0
   297.5    .045       0  316.31     .06       0  376.35      .1       0
Bank Sta=297.5,316.31
XS Rating Curve= 0 ,0
Exp/Cntr(USF)=0,0
Exp/Cntr=0.3,0.1

Type RM Length L Ch R = 1 ,2508    ,446.9,449.1,450.3
XS GIS Cut Line= 6
1626974.65799217409561.5532221791627001.53096992409652.682633087
1627026.24712785409737.5984737581627049.94393083409808.968081668
1627088.30409034409901.317962587  1627186.601794410137.964470923
#Sta/Elev= 30
       0  858.77      24   845.7    36.5  842.37    44.8  838.44    65.7  821.78
      74  810.32    78.2  806.57    94.9  798.36   115.7  785.06   132.4  777.17
   157.3  775.67   212.6  776.22   279.8  775.09   302.8  771.01   310.2   770.4
  315.44 771.048   324.2  774.46   340.5  775.52   370.1  800.31   392.5  809.51
   431.4   837.4   452.8  847.21   483.4   864.4   505.7  879.87   518.1  886.62
   526.7  889.82   544.1  892.97   591.7  905.57   600.4  909.55   614.9  920.77
#Mann= 4 ,-1,0
       0      .1       0   302.8    .045       0  315.44     .06       0
  418.65      .1       0
Bank Sta=302.8,315.44
XS Rating Curve= 0 ,0
Exp/Cntr(USF)=0,0
Exp/Cntr=0.3,0.1

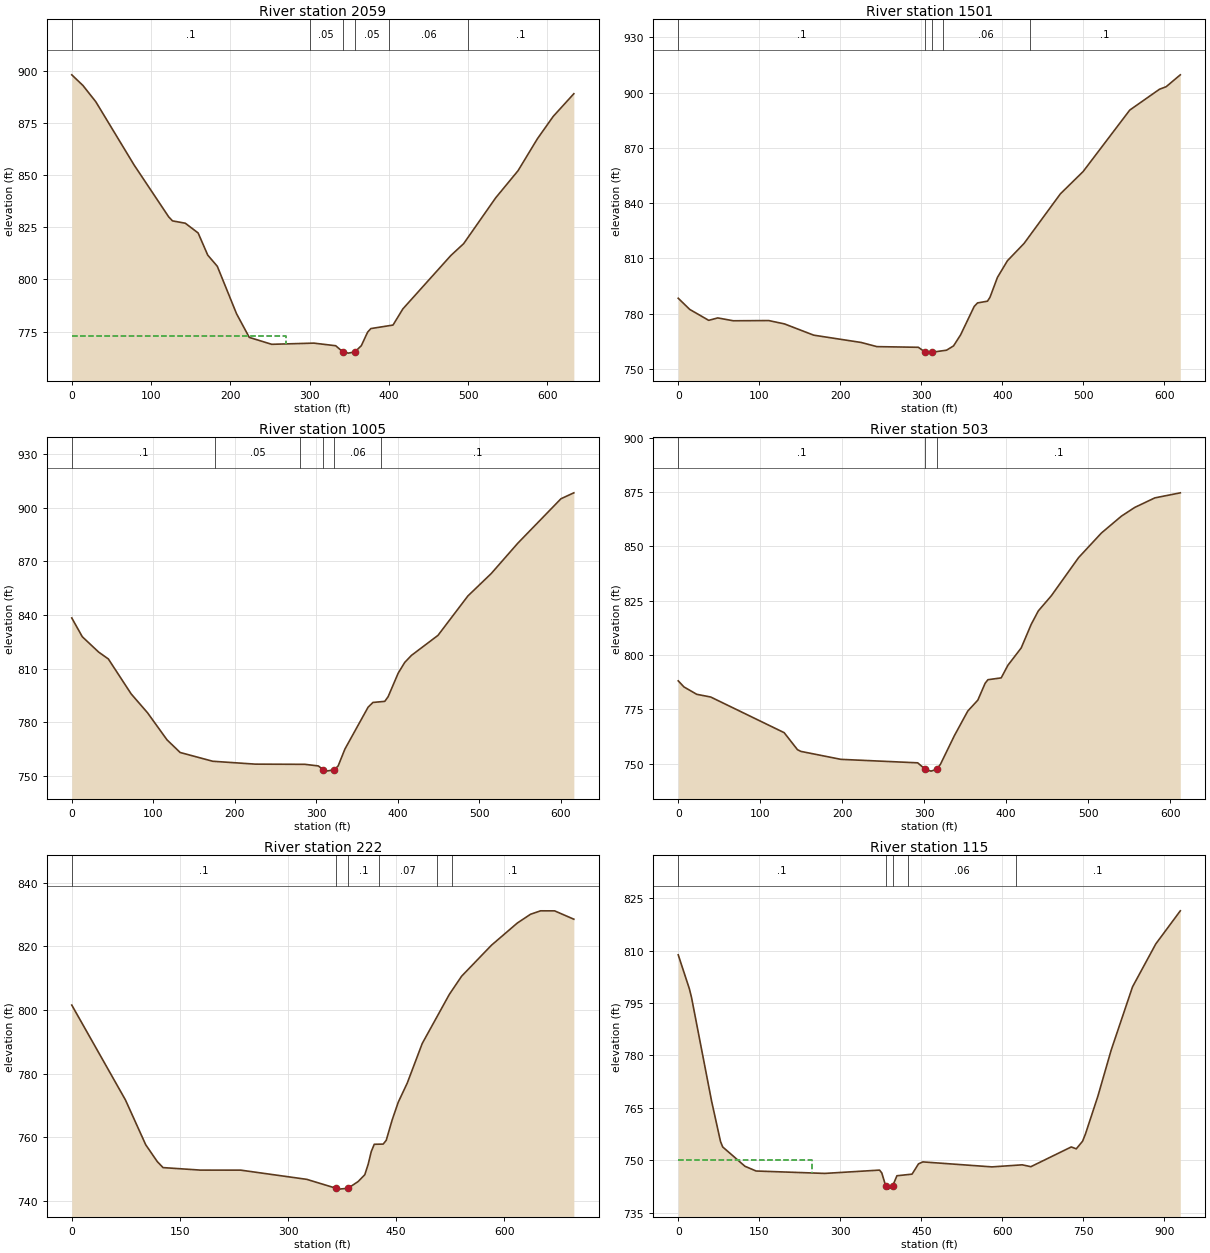
Type RM Length L Ch R = 1 ,2059    ,559.4,558.5,556.3
XS GIS Cut Line= 2
1626615.28724664409658.5259352541626698.37577926410286.305959479
#Sta/Elev= 30
       0  898.21    14.1  893.09    30.3   885.3    78.7  854.89   122.3  830.02
   127.1  828.11   143.2  826.99   159.4  822.31   171.5  811.69   183.6   806.3
   207.8  783.58   223.9  772.19   252.2  768.87   305.4  769.44   332.9  768.19
   341.6  765.37     349  764.64   357.1  765.25   365.2  768.19   373.2  774.72
   377.3  776.43   405.2  778.11   417.6  785.85   478.1  811.47   494.3  817.18
   534.6  839.12   562.9  852.19   587.3   867.5   607.3  878.27   633.3  889.14
#Mann= 6 ,-1,0
       0      .1       0     300     .05       0   341.6    .045       0
   357.1     .05       0     400     .06       0     500      .1       0
#XS Ineff= 2 , 0
          269.92  772.82
Permanent Ineff=
       F       F
Bank Sta=341.6,357.1
XS Rating Curve= 0 ,0
Exp/Cntr(USF)=0,0
Exp/Cntr=0.3,0.1

Type RM Length L Ch R = 1 ,1501    ,494.5,495.8,496.8
XS GIS Cut Line= 6
1625993.53068934409860.3416665941626112.16004525410087.630582094
1626151.02512501410179.9145182521626167.65665342 410255.16436775
1626185.48010859410343.4896504281626203.64444233410437.757506505
#Sta/Elev= 30
       0  788.32    14.2  782.26    37.6  776.32    48.8  777.64    67.9  776.09
   111.7   776.2   131.1  774.39   167.2  768.27   225.8   764.3   245.2  762.04
   296.4  761.68   304.6  759.08     309  758.51   313.8  759.03   331.2  760.11
   339.8  762.44   348.5  768.42   365.3  783.88   369.4  785.78   381.7  786.74
   384.8  788.86     394  799.66   406.3   808.7   426.8  818.08   471.7  845.06
   499.7  857.14   557.3  890.55     594  901.88   602.2  903.24   619.7  909.71
#Mann= 5 ,-1,0
       0      .1       0   304.6    .045       0   313.8      .1       0
  326.38     .06       0  433.58      .1       0
Bank Sta=304.6,313.8
XS Rating Curve= 0 ,0
Exp/Cntr(USF)=0,0
Exp/Cntr=0.3,0.1

Type RM Length L Ch R = 1 ,1005    ,501.4,502.1,501.2
XS GIS Cut Line= 6
1625641.40048809409975.6268690821625642.97331959410071.379630342
1625646.74299709410160.0874581781625656.36600934410234.648004591
1625707.84720559410492.0503769221625726.23365176410583.979655012
#Sta/Elev= 30
       0  838.29    12.9  827.79    32.9  819.22    44.9  815.34    72.9  795.78
    92.9  785.27   116.9  770.07     133  763.01     173  758.11   225.2   756.5
   286.1  756.39   302.5  755.49   308.7  753.37   312.1  752.59   322.3  753.36
   326.9  755.57   335.1  764.91   363.6  788.38   369.5  791.01     384  791.62
   388.1   794.2   400.5  807.41   408.5   813.4   416.7  817.32   449.3  828.54
     486  850.59   514.6  863.11   547.2  880.08   600.2  904.98     616  908.29
#Mann= 6 ,-1,0
       0      .1       0  175.77     .05       0  279.73     .06       0
   308.7    .045       0   322.3     .06       0  379.73      .1       0
Bank Sta=308.7,322.3
XS Rating Curve= 0 ,0
Exp/Cntr(USF)=0,0
Exp/Cntr=0.3,0.1

Type RM Length L Ch R = 1 ,503     ,274.7,280.6,283.2
XS GIS Cut Line= 6
1625120.50881334 410005.674709261625154.78564768410183.654012084
1625187.88105392410355.496188089 1625202.0644245410429.142694339
1625218.61261976410515.0637823341625236.34125884410607.122325256
#Sta/Elev= 30
       0  788.18       7  785.37    22.6  781.98    39.6  780.74   129.2  764.34
   145.5   756.5   149.6  755.72   198.4  752.06   292.1  750.46  301.37747.4899
   308.4  746.64   315.2  747.47   319.8  749.73   336.8   762.9   353.2  774.27
   365.5  779.31   374.4  787.06   377.8   788.7     394  789.54   402.1   795.3
   418.4  803.32   430.6  814.17   439.3  820.36   455.1   827.3   488.4  844.88
   516.2  856.17   540.6  863.94   556.9  867.96   581.4  872.35   612.5  874.68
#Mann= 3 ,-1,0
       0      .1       0  301.37    .045       0   315.2      .1       0
Bank Sta=301.37,315.2
XS Rating Curve= 0 ,0
Exp/Cntr(USF)=0,0
Exp/Cntr=0.3,0.1

Type RM Length L Ch R = 1 ,222     ,111.4,107.7,105.1
BEGIN DESCRIPTION:
Low water crossing
END DESCRIPTION:
XS GIS Cut Line= 6
1624958.77056575410034.0649018321624946.24984027410316.476820997
1624932.33792307410377.6892566791624917.03481415 410416.64262484
1624905.90528039 410431.945733761624987.98559187410710.184077765
#Sta/Elev= 30
       0  801.58    74.5  771.78   102.6  757.72   118.6  752.45   126.6  750.55
   178.6  749.76   234.4  749.75     326  746.86  367.18744.0265   370.2  743.79
   383.1  744.04   397.3  746.18   406.5  748.31   411.2   751.6   415.4  755.54
   419.6  757.87     432  757.93   436.2   759.1   444.5  765.54   452.9  771.08
   465.4  777.09   486.2  789.53   523.8  804.94   540.8  810.64   582.2  820.37
   618.1  827.34   636.4  830.09   650.3  831.17   669.8  831.16   696.5  828.54
#Mann= 6 ,-1,0
       0      .1       0  367.18    .045       0   383.1      .1       0
  426.46     .07       0  506.84     .06       0  526.84      .1       0
Bank Sta=367.18,383.1
XS Rating Curve= 0 ,0
Exp/Cntr(USF)=0,0
Exp/Cntr=0.3,0.1

Type RM Length L Ch R = 1 ,115     ,,,
XS GIS Cut Line= 4
1624847.39855681410028.5730753241624807.89558204410188.302495031
1624823.35326782410772.2595133141624989.95277009410842.677859637
#Sta/Elev= 30
       0  808.82    20.6  799.11    24.7  796.54    61.8   766.9    78.3  755.34
    82.4  753.79   123.6  748.26   144.2  746.91   271.4  746.22   372.8  747.17
   376.9  746.35  384.02742.7156   388.9  741.72   396.9  742.59   404.9  745.55
   432.9  746.01   444.9  748.96   452.9  749.52   580.9  748.09   636.9  748.68
   652.9  748.15   727.7   753.8     737  753.26   748.7  755.46   753.9  757.48
     777  768.35   801.6  781.54   841.1  799.65   884.2  811.95   929.6  821.43
#Mann= 5 ,-1,0
       0      .1       0  384.02    .045       0   396.9      .1       0
  424.54     .06       0  624.54      .1       0
#XS Ineff= 2 , 0
          247.43  750.14
Permanent Ineff=
       F       F
Bank Sta=384.02,396.9
XS Rating Curve= 0 ,0
Exp/Cntr(USF)=0,0
Exp/Cntr=0.3,0.1
LCMann Table=0

Chan Stop Cuts=-1
Use User Specified Reach Order=0
Composite Channel Slope=5